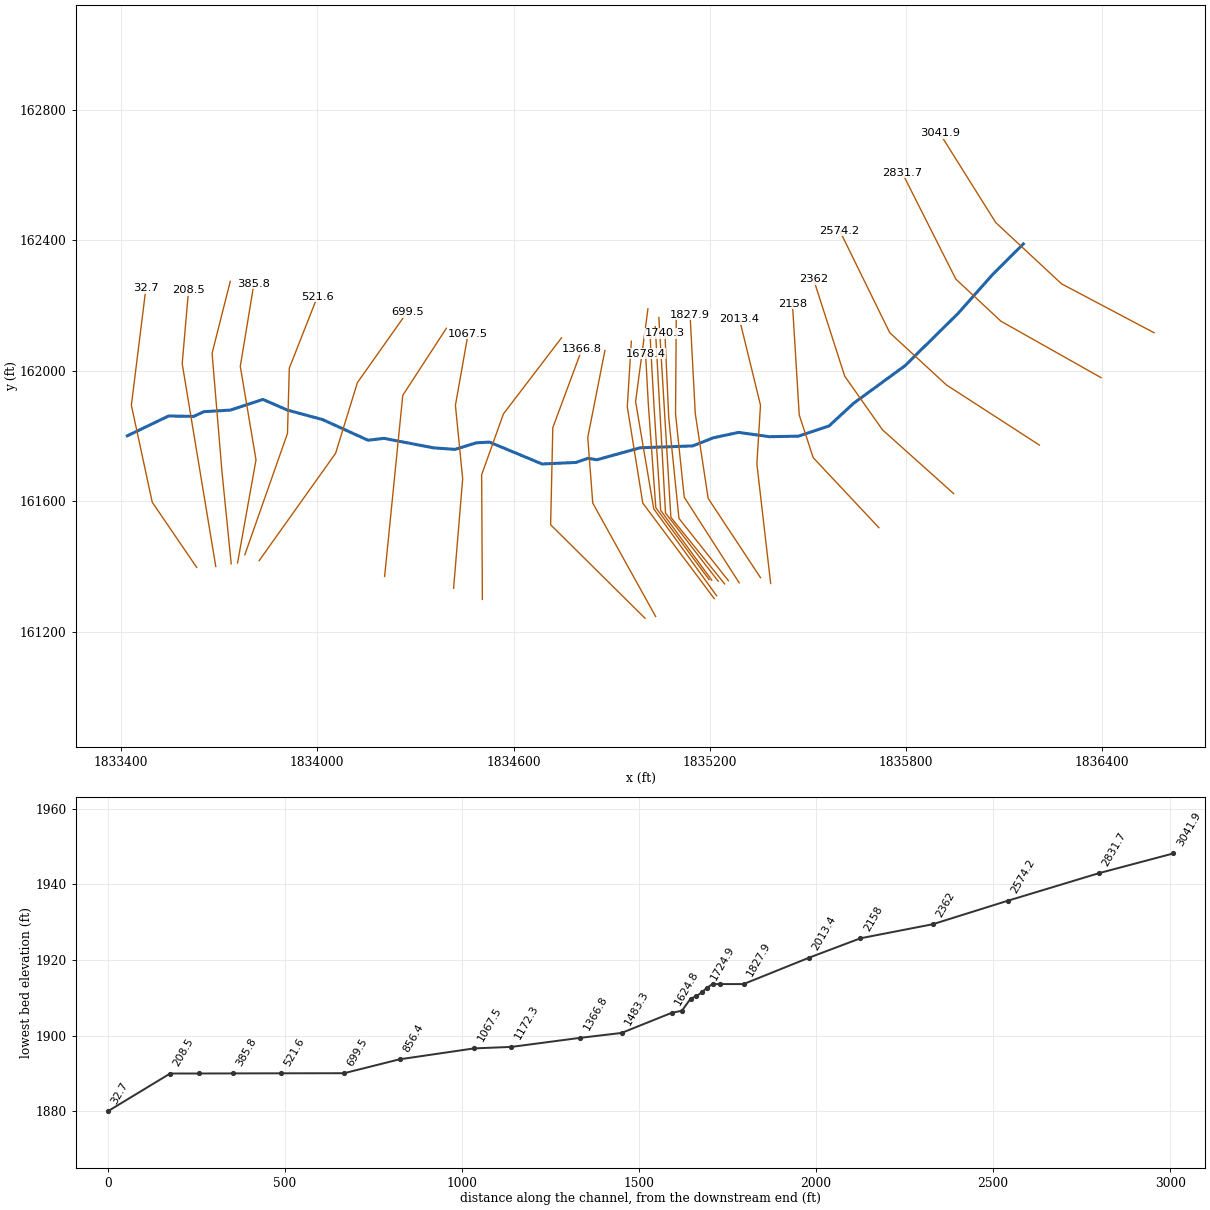
--- Bottom Creek Trib 1.prj (project) ---

Proj Title=Bottom Creek Trib 1
Current Plan=p01
Default Exp/Contr=0,0
English Units
Geom File=g01
Flow File=f01
Plan File=p01
BEGIN DESCRIPTION:
END DESCRIPTION:
DSS Export Rating Curves= 0
DSS Export Rating Curve Sorted= 0
DSS Export Volume Flow Curves= 0
DXF OffsetX= 0
DXF OffsetY= 0
DXF ScaleX= 0
DXF ScaleY= 0

--- Bottom Creek Trib 1.p01 (plan) ---

Plan Title=Floodplain
Program Version=4.00
Geom File=g01
Flow File=f01
K Sum by GR=0
Std Step Tol=0.01
Critical Tol=0.01
Num of Std Step Trials=20
Max Error Tol=0.3
Flow Tol Ratio=0.001
Split Flow NTrial=30
Split Flow Tol=0.02
Split Flow Ratio=0.02
Log Output Level=0
Friction Slope Method=1
Unsteady Friction Slope Method=2
Unsteady Bridges Friction Slope Method=1
Global Log Level=0
CheckData=False
Run HTab=0
Run UNet=0
Run PostProcess=0
UNET Theta=0
UNET Theta Warmup=0
UNET ZTol=0
UNET ZSATol=0
UNET MxIter=0
UNET MaxInSteps=0
UNET DtIC=0
UNET DtMin=0
UNET MaxCRTS=0
UNET WFStab=0
UNET SFStab=0
UNET WFX=0
UNET SFX=0
UNET DSS MLevel=0
UNET DZMax Abort=0
UNET Convert EG Bridges=0
UNET Use Existing IB Tables=0
UNET Froude Limit=0
UNET Froude Power=0
Write IC File=0
Echo Input=False
Echo Output=False
Write Detailed=0

--- Bottom Creek Trib 1.f01 (steady flow) ---

Flow Title=NFF Regression Equation
Program Version=4.00
Number of Profiles=1
Profile Names=P100yr
River Rch & RM=Bottom Creek ...,Main      ,3041.9
561.3093
River Rch & RM=Bottom Creek ...,Main      ,1483.3
597.1176
River Rch & RM=Bottom Creek ...,Main      ,1172.3
716.8755
River Rch & RM=Bottom Creek ...,Main      ,291.3
738.9419
Boundary for River Rch & Prof#=Bottom Creek ...,Main      ,1
Up Type=0
Dn Type=3
Dn Slope=0.018028

--- Bottom Creek Trib 1.g01 (geometry) ---

Geom Title=USGS 10m DEM
Program Version=4.00

River Reach=Bottom Creek ...,Main
Reach XY= 30
     1836158.937      162388.098     1836067.148      162296.905
     1835958.924      162174.907     1835797.178      162015.129
     1835639.456      161899.574     1835565.011      161830.561
     1835471.149      161799.183     1835382.442      161797.581
     1835288.371      161810.727     1835210.474      161794.047
     1835148.047      161769.312     1834987.267       161763.59
     1834854.905      161726.877      1834827.62      161731.329
     1834791.154      161718.664     1834687.502      161713.952
      1834526.39      161780.966     1834486.087      161778.735
     1834421.304      161758.711     1834355.344      161763.423
     1834204.204      161792.449     1834155.016      161786.841
     1834015.995      161850.032     1833908.872      161879.029
     1833833.837      161911.737     1833733.789      161879.029
     1833652.982      161874.219     1833622.198      161859.789
     1833545.239      161860.961     1833418.944      161800.219

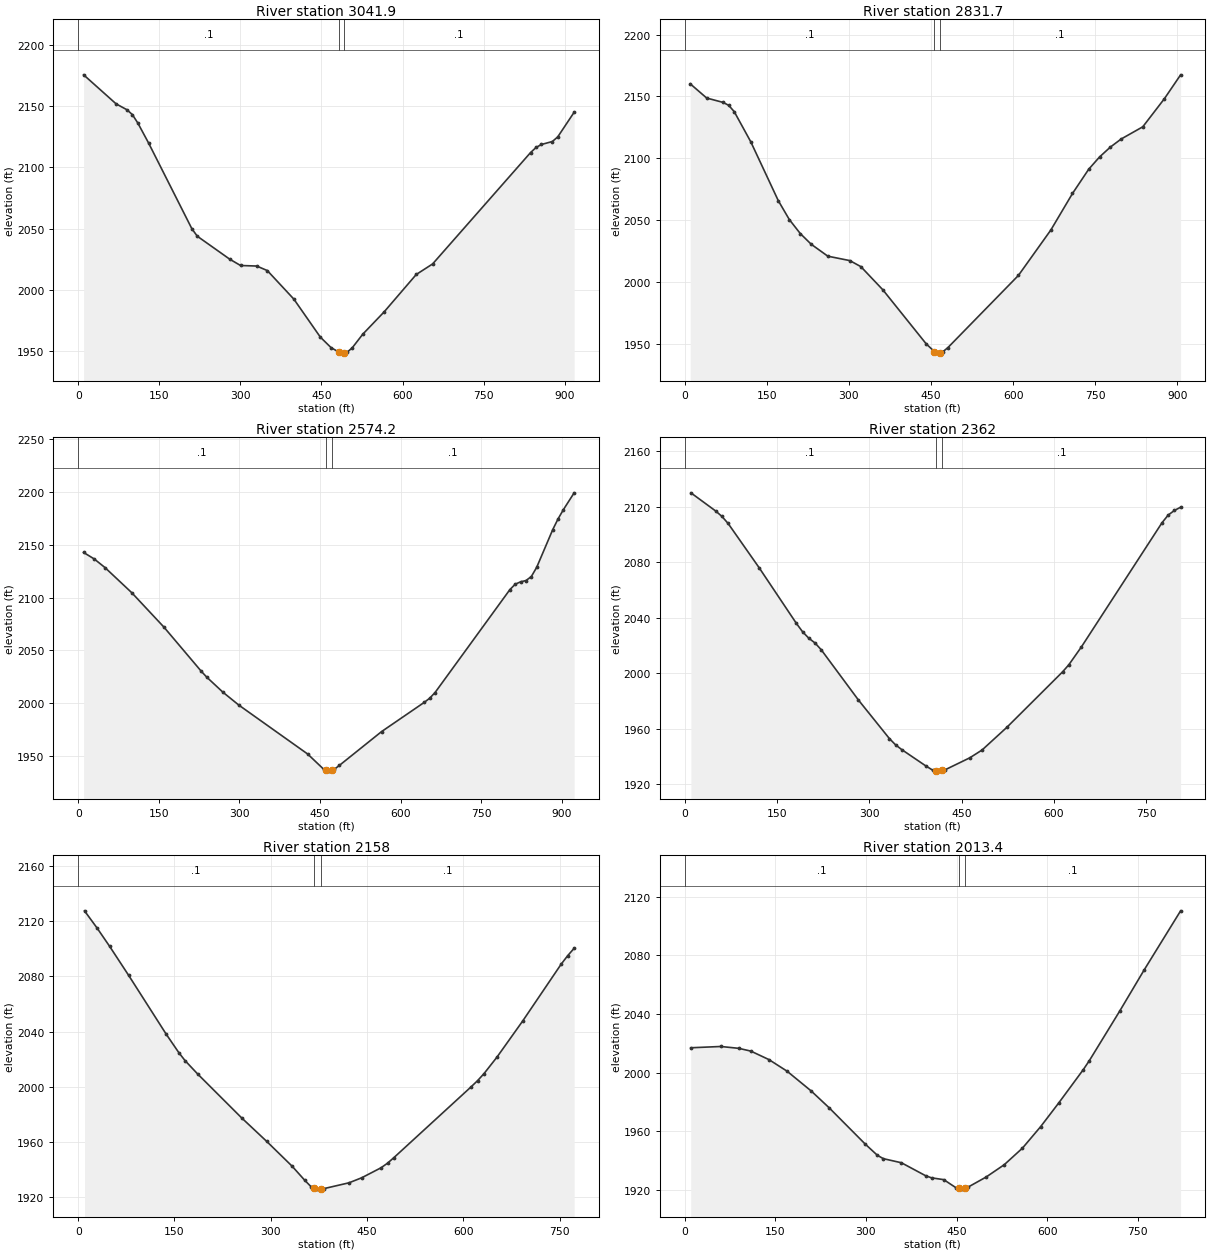
Type RM Length L Ch R = 1 ,3041.9  ,210.3,210.2,210.2
XS GIS Cut Line= 4
     1836558.697      162116.105     1836275.588      162266.063
     1836074.644       162453.61     1835903.672      162726.722
#Sta/Elev= 30
      10 2175.75    70.1 2152.01    90.1  2147.2   100.1 2143.26   110.1 2136.48
   130.2 2119.98   210.2 2049.94   220.3 2043.77   280.3    2025   300.3 2019.83
   330.2 2019.39   349.8 2015.69   398.9 1992.36     448 1961.23   467.6 1952.74
   482.3 1948.97   487.3 1948.17   492.3 1948.48   497.1 1948.78   506.9 1952.48
   526.5 1963.68   565.8 1981.82   625.4 2012.49   655.7 2021.12   836.9  2112.2
     847 2116.33     857 2118.79   877.2 2121.22   887.2 2125.03   917.5 2145.17
#Mann= 3 , 0 , 0
       0      .1       0   482.3    .045       0   492.3      .1       0
Bank Sta=482.3,492.3
XS Rating Curve= 0 ,0
Exp/Cntr=0.3,0.1

Type RM Length L Ch R = 1 ,2831.7  ,257.4,257.5,257.6
XS GIS Cut Line= 4
     1836396.606      161978.439     1836090.187      162151.632
     1835952.521      162280.416     1835788.209      162606.819
#Sta/Elev= 30
    10.1 2160.22    40.2 2148.75    70.4 2145.19    80.5 2142.82    90.5 2137.78
   120.7 2113.48     171 2065.94   191.1 2050.74   211.2  2039.4   231.3 2030.72
   261.5 2021.15   301.7 2017.59   321.8 2012.74   361.9 1994.07   441.3 1950.36
   456.1 1944.24   461.1 1942.95   466.1 1943.39     471 1943.82     481 1947.49
   609.6 2005.63   668.9 2042.31   708.4 2071.75     738  2091.3   757.8  2101.2
   777.5 2109.15   797.3 2115.69   836.8 2125.54   876.3 2148.23   905.9 2167.47
#Mann= 3 , 0 , 0
       0      .1       0   456.1    .045       0   466.1      .1       0
Bank Sta=456.1,466.1
XS Rating Curve= 0 ,0
Exp/Cntr=0.3,0.1

Type RM Length L Ch R = 1 ,2574.2  ,216.5,212.2,207.9
XS GIS Cut Line= 4
      1836207.87      161771.939     1835923.655      161956.234
     1835750.462      162116.105     1835597.253      162429.185
#Sta/Elev= 30
      10  2142.9    29.9 2136.71    49.8  2128.6    99.6 2104.79   159.4 2072.22
   229.1 2030.26   239.1 2024.79     269 2010.61   298.9 1998.25   427.1 1951.85
   456.6 1937.55   461.4 1936.62   466.4 1935.66   471.4 1936.46   476.2 1937.23
     486 1941.06   564.6 1973.13   644.1 2000.85   654.1 2004.75   664.1 2010.12
   803.5 2107.76   813.4 2112.85   823.4 2115.07   833.4 2116.29   843.3 2120.07
   853.3 2128.83   883.2 2164.59   893.1 2174.77   903.1 2183.58     923 2199.42
#Mann= 3 , 0 , 0
       0      .1       0   461.4    .045       0   471.4      .1       0
Bank Sta=461.4,471.4
XS Rating Curve= 0 ,0
Exp/Cntr=0.3,0.1

Type RM Length L Ch R = 1 ,2362    ,210.1,204,198
XS GIS Cut Line= 4
      1835945.86      161623.171     1835728.258      161818.568
     1835612.796      161982.879     1835517.317      162280.416
#Sta/Elev= 30
    10.1 2130.09    50.4 2116.98    60.5 2113.09    70.6 2107.99     121 2076.08
   181.5 2035.96   191.6 2029.89   201.7 2025.26   211.8 2021.83   221.9 2016.93
   282.4 1980.66   332.6 1952.92   342.7 1948.38   352.7 1944.96   392.9 1932.87
   402.9 1930.18     408  1929.8   412.9 1929.44     418 1929.91     423 1930.37
   463.2 1939.03   483.2 1944.67   523.5 1961.03   614.2  2001.1   624.3  2006.2
   644.5 2018.93   775.5 2108.48   785.6 2114.06   795.7 2117.37   805.8 2119.73
#Mann= 3 , 0 , 0
       0      .1       0     408    .045       0     418      .1       0
Bank Sta=408,418
XS Rating Curve= 0 ,0
Exp/Cntr=0.3,0.1

Type RM Length L Ch R = 1 ,2158    ,152.1,144.6,137
XS GIS Cut Line= 4
     1835717.156       161518.81     1835516.365      161733.323
      1835473.64       161864.55     1835452.925      162204.922
#Sta/Elev= 30
     9.8 2127.57    29.4 2115.09      49 2101.78    78.4 2080.91   137.1 2038.12
   156.7 2024.77   166.5 2018.93   186.1 2009.25   254.6 1977.43   293.8 1960.32
   333.3 1942.37     353 1932.14   362.8  1927.5   367.7 1926.62   372.7 1925.73
   377.7  1925.9   382.5 1926.06     422 1930.32   441.9    1934   471.9 1941.22
     482 1944.55     492 1948.61   612.4 1999.99   622.4 2004.45   632.4 2009.54
   652.5 2021.45   692.6 2047.66   752.8 2089.05   762.8 2095.08   772.8 2100.41
#Mann= 3 , 0 , 0
       0      .1       0   367.7    .045       0   377.7      .1       0
Bank Sta=367.7,377.7
XS Rating Curve= 0 ,0
Exp/Cntr=0.3,0.1

Type RM Length L Ch R = 1 ,2013.4  ,181.2,185.5,189.9
XS GIS Cut Line= 4
     1835386.312      161347.838     1835344.124      161714.208
     1835355.226      161894.062     1835290.834      162158.293
#Sta/Elev= 30
      10 2016.99    59.8 2017.87    89.7  2016.6   109.6 2014.71   139.5 2008.93
   169.4 2001.06   209.3 1987.59   239.2 1976.06     299 1951.29     319 1943.69
   328.9 1941.39   358.8  1938.6   398.8 1929.77   408.8  1928.3   428.9 1927.08
   448.9 1921.63   453.9 1921.12   458.9 1920.62   463.9 1921.28   468.9 1921.94
   498.9 1928.83     529 1937.26   559.1 1948.54   589.3 1963.23   619.5 1979.52
   659.8 2002.05   669.9 2008.23   720.2 2042.04   760.5 2069.97     821 2110.36
#Mann= 3 , 0 , 0
       0      .1       0   453.9    .045       0   463.9      .1       0
Bank Sta=453.9,463.9
XS Rating Curve= 0 ,0
Exp/Cntr=0.3,0.1

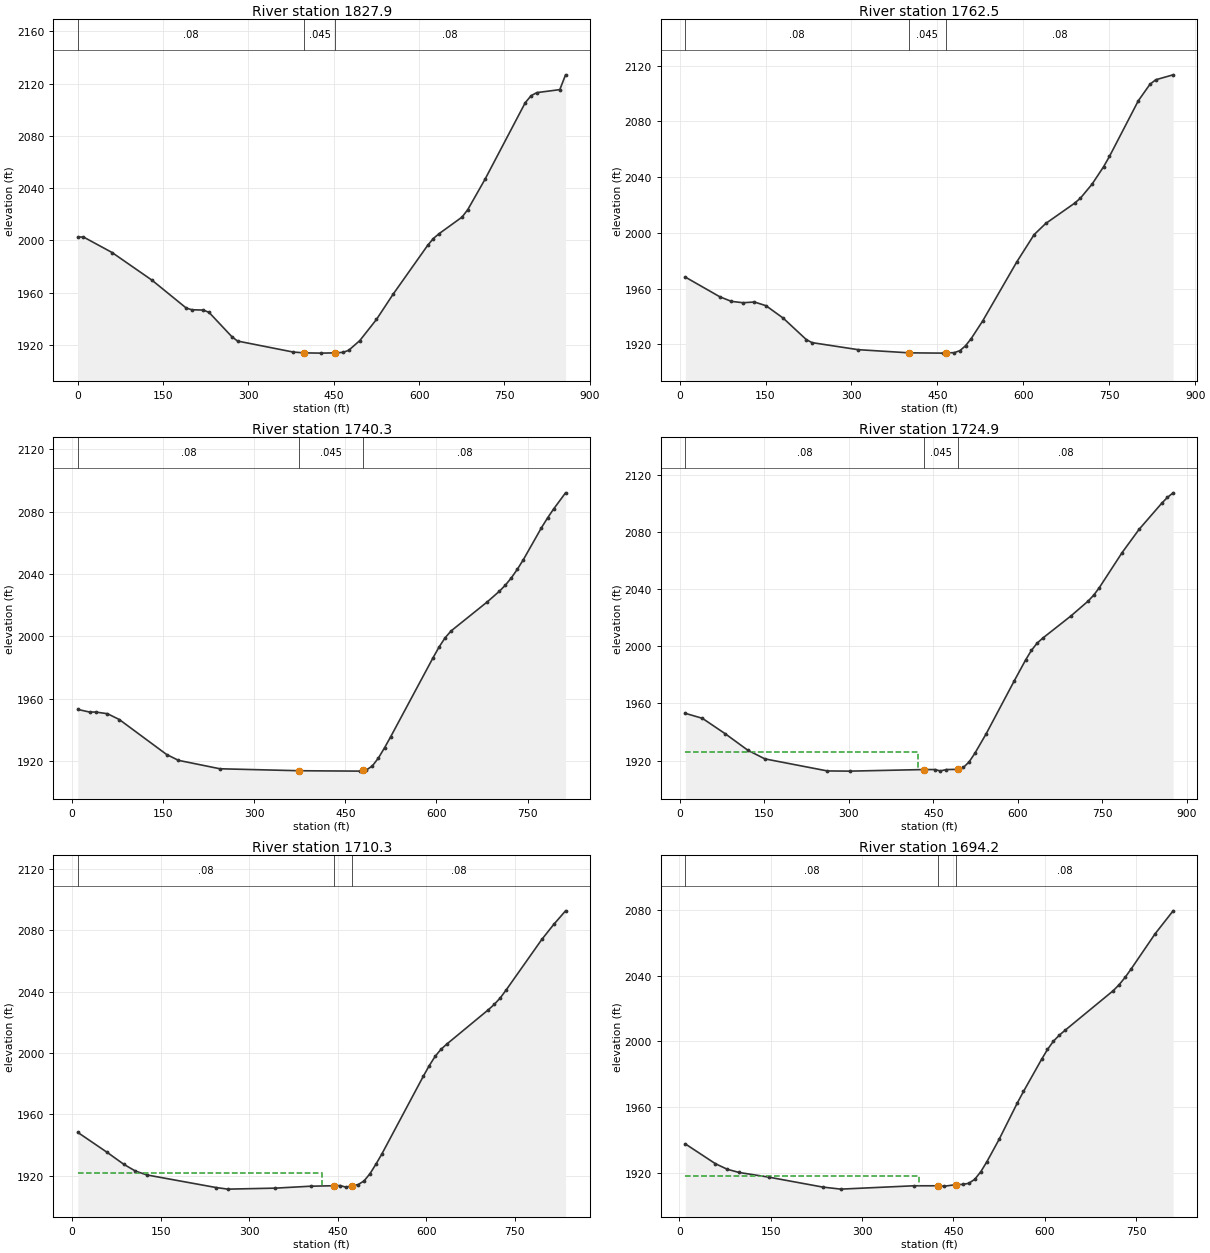
Type RM Length L Ch R = 1 ,1827.9  ,67.4,65.4,63.4
XS GIS Cut Line= 4
     1835355.226      161365.601     1835195.203      161608.463
     1835155.746       161868.88     1835139.845      162171.616
#Sta/Elev= 30
       0 2002.49      10 2002.49    60.2 1990.65   130.4 1969.46   190.6 1948.14
   200.6 1946.81   220.6 1946.59   230.7 1944.81   270.8 1926.22   280.8 1922.87
   378.6 1914.45   398.1 1913.81  427.37 1913.62   451.9 1913.81   466.4 1914.22
   476.2 1915.79   495.7 1923.22     525  1939.4   554.2 1958.68   614.9 1996.05
     625 2001.36   635.1 2005.06   675.5 2017.78   685.6 2023.55   715.9 2046.77
   786.6 2105.37   796.8 2110.68   806.9 2113.04   847.3 2115.33   857.4 2126.66
#Mann= 3 , 0 , 0
       0     .08       0   398.1    .045       0   451.9     .08       0
Bank Sta=398.1,451.9
XS Rating Curve= 0 ,0
Exp/Cntr=0.3,0.1

Type RM Length L Ch R = 1 ,1762.5  ,22.3,22.2,22.2
XS GIS Cut Line= 4
     1835290.188      161349.669     1835122.082      161612.068
     1835095.437      161867.417     1835097.657      162160.513
#Sta/Elev= 30
    10.1  1968.2    70.4 1954.04    90.5 1950.78   110.6 1949.81   130.7 1950.31
   150.8 1947.68   180.9 1938.75   221.2 1923.35   231.2 1921.16   311.6 1916.11
   400.5 1913.83   460.2 1913.62   464.7  1913.8   479.5 1913.96   489.4 1915.41
   499.2 1918.93   509.1 1924.09   528.9 1936.59   588.6  1979.1   618.9  1998.7
   639.1 2006.69   689.6 2021.27   699.8 2024.93     720 2034.92   740.2 2047.48
   750.3  2054.8   800.8 2094.85     821 2106.59   831.1 2109.88   861.5 2113.43
#Mann= 3 , 0 , 0
    10.1     .08       0   400.5    .045       0   464.7     .08       0
Bank Sta=400.5,464.7
XS Rating Curve= 0 ,0
Exp/Cntr=0.3,0.1

Type RM Length L Ch R = 1 ,1740.3  ,16.2,15.4,14.6
XS GIS Cut Line= 4
     1835257.276      161356.252      1835105.88      161547.142
     1835074.613      161856.516     1835062.994      162114.095
#Sta/Elev= 30
     9.7 1953.19    29.2  1951.5      39 1951.53    58.5 1950.45      78 1946.72
   155.9 1924.27   175.4 1920.53   243.6 1915.12     374 1913.86   474.3 1913.61
   479.3 1914.03   484.4 1914.29   494.4 1916.92   504.4 1922.03   514.5 1928.58
   524.5 1935.59   594.3 1986.34   604.2  1993.2   614.1 1999.12     624 2003.55
   683.5 2022.18   703.3 2028.96   713.3 2032.91   723.2 2037.62   733.1 2043.15
     743 2049.32   772.8 2069.82   782.7 2076.02   792.6 2081.71   812.4 2092.17
#Mann= 3 , 0 , 0
     9.7     .08       0     374    .045       0   479.3     .08       0
Bank Sta=374,479.3
XS Rating Curve= 0 ,0
Exp/Cntr=0.3,0.1

Type RM Length L Ch R = 1 ,1724.9  ,14.7,14.6,14.5
XS GIS Cut Line= 4
     1835245.756      161346.378     1835081.196      161550.433
     1835063.094      161851.579     1835044.367      162162.734
#Sta/Elev= 30
    10.1 1953.08    40.3 1949.61    80.7 1938.87     121 1927.29   151.2 1921.26
   262.1 1912.83   302.4  1912.7   433.1  1913.8   453.2  1913.8  462.37 1912.83
   473.3  1913.8   493.4 1913.94   503.5 1915.29   513.6 1919.16   523.6 1925.03
   543.7 1938.67     594    1976   614.1 1990.56   624.2  1997.1   634.2 2002.12
   644.3 2005.66   694.6 2021.25   724.7 2031.51   734.8 2035.73   744.8 2041.02
   785.1 2065.43   815.2 2081.66   855.4 2099.92   865.5    2104   875.6  2107.2
#Mann= 3 , 0 , 0
    10.1     .08       0   433.1    .045       0   493.4     .08       0
#XS Ineff= 2 , 0
          422.13 1926.09
Permanent Ineff=
       F       F
Bank Sta=433.1,493.4
XS Rating Curve= 0 ,0
Exp/Cntr=0.3,0.1

Type RM Length L Ch R = 1 ,1710.3  ,15.9,16.1,16.3
XS GIS Cut Line= 4
     1835226.009      161354.606      1835064.74      161563.598
     1835044.992      161923.986     1835033.473      162134.623
#Sta/Elev= 30
     9.8 1948.34    58.7 1935.57      88 1927.52   107.5 1923.17   127.1 1920.65
   244.4 1912.45     264 1911.44   344.2 1912.08   404.3 1913.34   444.4 1913.66
   454.5 1913.74  464.23 1912.67   474.5 1913.77   484.5 1914.37   494.6 1916.77
   504.6 1921.46   514.6 1927.59   524.7 1934.26   594.8 1984.75   604.9 1991.66
   614.9 1997.74   624.9  2002.4     635 2005.87   705.3 2028.17   715.3 2031.67
   725.4 2035.87   735.4 2041.05   795.7 2073.88   815.8  2083.6   835.9 2092.48
#Mann= 3 , 0 , 0
     9.8     .08       0   444.4    .045       0   474.5     .08       0
#XS Ineff= 2 , 0
          423.93 1921.67
Permanent Ineff=
       F       F
Bank Sta=444.4,474.5
XS Rating Curve= 0 ,0
Exp/Cntr=0.3,0.1

Type RM Length L Ch R = 1 ,1694.2  ,15.6,15.8,16
XS GIS Cut Line= 4
     1835206.262      161357.897     1835049.929      161571.826
     1835030.182        161881.2     1835017.017      162116.521
#Sta/Elev= 30
     9.8 1937.83    58.9 1925.89    78.5 1922.47    98.1  1920.5   147.2 1917.65
   235.5 1911.64     265  1910.4     385 1912.43     425 1912.43   435.1 1912.15
     455 1913.19     465 1913.26     475 1913.91     485 1916.36     495 1921.01
     505  1927.1     525 1940.62     555 1962.77     565 1969.66   594.6 1989.08
   604.4 1995.14   614.2  2000.2   624.1 2003.92   633.9 2006.98   712.5 2030.88
   722.3 2034.57   732.1 2039.03   741.9 2044.08   781.2 2065.39   810.7  2079.3
#Mann= 3 , 0 , 0
     9.8     .08       0     425    .045       0     455     .08       0
#XS Ineff= 2 , 0
          393.55 1918.62
Permanent Ineff=
       F       F
Bank Sta=425,455
XS Rating Curve= 0 ,0
Exp/Cntr=0.3,0.1

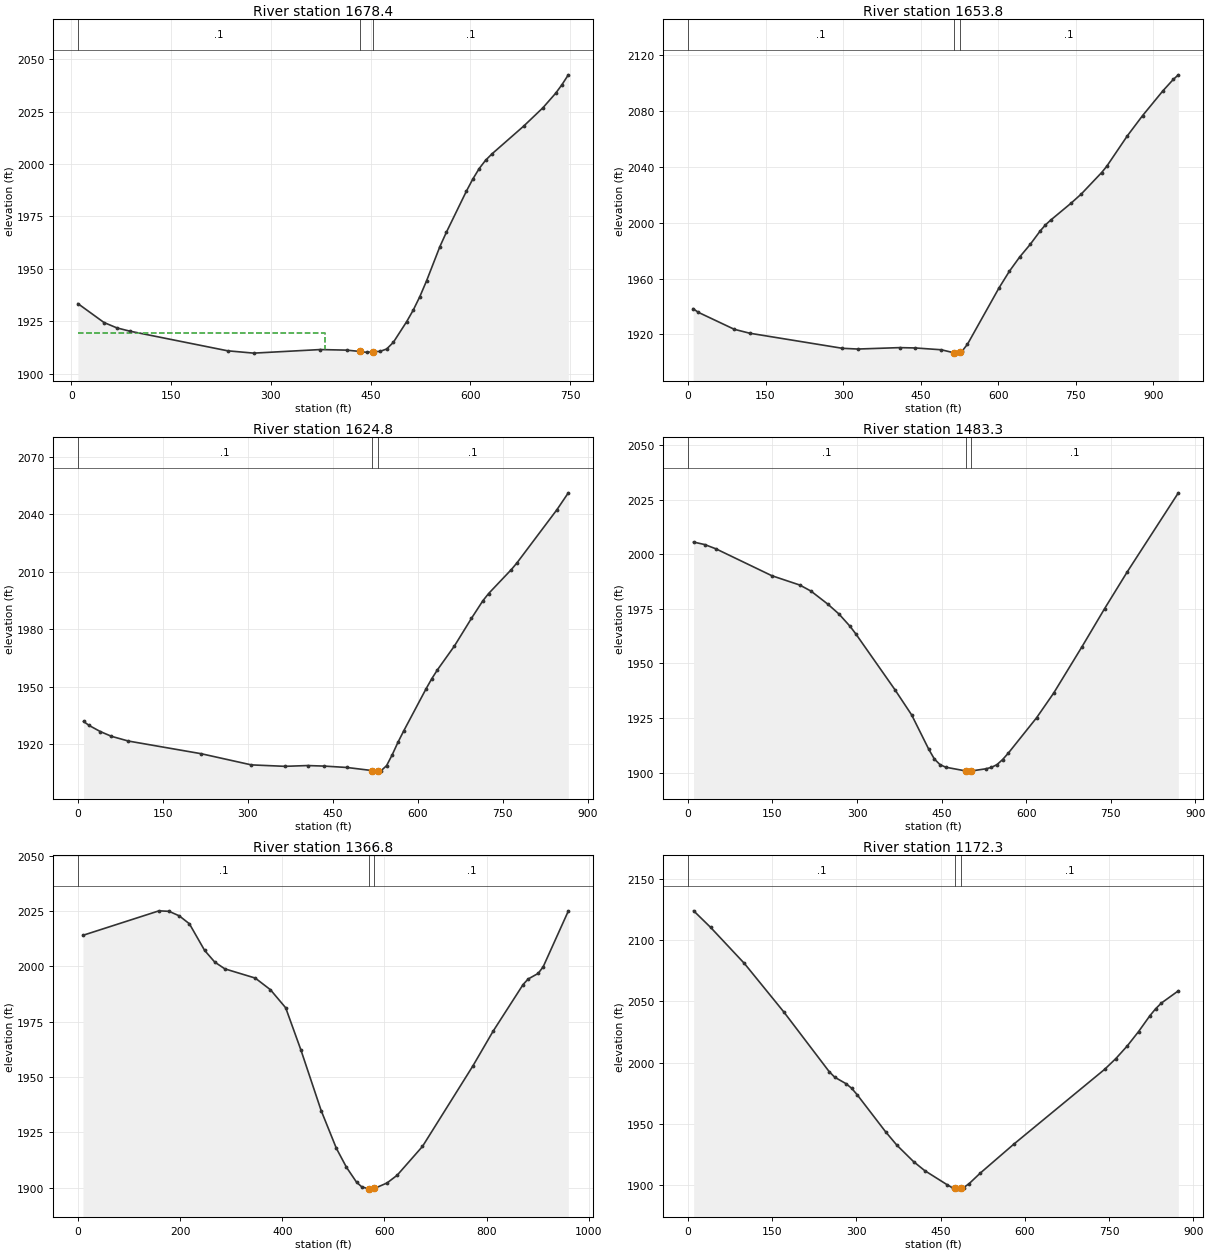
Type RM Length L Ch R = 1 ,1678.4  ,22.7,24.6,26.6
XS GIS Cut Line= 4
     1835198.034      161359.543     1835035.119      161580.054
      1835012.08      161899.301     1835003.852      162052.343
#Sta/Elev= 30
     9.8  1933.4      49 1924.39    68.5 1921.81    88.1 1920.24     235 1910.89
   274.2 1909.78   374.2 1911.48   414.2 1911.21   434.2 1910.57   444.2 1910.15
   454.2 1910.45   464.2 1910.61   474.2 1911.75   484.2  1914.9   504.2 1924.74
   514.2 1930.31   524.2  1936.8   534.2 1944.24   554.2 1960.55   564.2 1967.55
   594.2 1987.09   603.8 1992.83   613.4 1997.85     623  2001.8   632.6 2004.84
   680.5 2018.15   709.2 2026.84   728.3 2033.73   737.9 2037.87   747.5 2042.58
#Mann= 3 , 0 , 0
     9.8      .1       0   434.2    .045       0   454.2      .1       0
#XS Ineff= 2 , 0
           381.4 1919.34
Permanent Ineff=
       F       F
Bank Sta=434.2,454.2
XS Rating Curve= 0 ,0
Exp/Cntr=0.3,0.1

Type RM Length L Ch R = 1 ,1653.8  ,29.1,29,28.8
XS GIS Cut Line= 4
     1835221.072      161310.175     1835028.824      161576.542
     1834973.313      161905.165      1835011.06      162189.379
#Sta/Elev= 30
      10 1938.41    19.9 1935.81    89.6 1923.63   119.5 1920.82   298.6 1910.03
   328.5  1909.5   409.3 1910.51   439.6 1910.27   490.1 1908.97   515.4 1906.73
   520.4 1906.57   525.4 1907.35   530.5 1908.15   540.6 1912.93   601.2 1953.01
   621.4 1965.06   641.6 1975.42   661.8 1984.37   681.5 1994.17   691.4 1998.37
   701.3 2001.74   740.9 2013.92   760.6 2020.46   800.2 2035.92   810.1 2040.42
   849.6 2062.06   879.3 2076.66   918.8 2094.49   938.6 2102.54   948.5 2105.87
#Mann= 3 , 0 , 0
       0      .1       0   515.4    .045       0   525.4      .1       0
Bank Sta=515.4,525.4
XS Rating Curve= 0 ,0
Exp/Cntr=0.3,0.1

Type RM Length L Ch R = 1 ,1624.8  ,143.2,141.5,139.9
XS GIS Cut Line= 4
     1835213.739      161301.382     1834995.268      161594.133
     1834947.902      161889.428     1834960.313      162090.063
#Sta/Elev= 30
     9.9 1931.94    19.7 1929.86    39.5 1926.66    59.2 1924.18    88.9 1921.72
   217.2 1915.12     306 1909.28   365.3 1908.52   405.2 1908.93   435.1 1908.64
   474.9 1907.92   519.8 1906.29   524.8 1906.02   529.8 1906.11   534.8 1906.19
   544.7 1908.89   554.7  1914.6   564.7 1921.03   574.6 1926.83   614.5 1949.05
   624.5 1954.26   634.4 1958.86   664.4 1971.31   694.5 1985.75   714.6 1994.91
   724.7 1998.66   764.9 2011.19   774.9 2014.72   845.3 2042.41   865.4 2051.21
#Mann= 3 , 0 , 0
       0      .1       0   519.8    .045       0   529.8      .1       0
Bank Sta=519.8,529.8
XS Rating Curve= 0 ,0
Exp/Cntr=0.3,0.1

Type RM Length L Ch R = 1 ,1483.3  ,118.4,116.5,114.6
XS GIS Cut Line= 4
     1835034.593      161246.764     1834842.338      161594.133
     1834827.045      161795.127     1834879.478      162061.662
#Sta/Elev= 30
     9.9 2005.57    29.8 2004.41    49.6 2002.47   148.9 1990.15   198.5 1985.88
   218.4  1983.1   248.1 1977.16     268 1972.62   287.8 1966.94   297.8 1963.54
   367.2    1938     397  1926.4   427.3  1910.7   437.3 1906.23   447.4 1903.64
   457.5 1902.49   492.8 1900.79   497.8  1900.7   502.8 1900.78     528 1901.74
   538.1 1902.38   548.2 1903.65   558.3 1905.99   568.4 1908.92   618.7 1925.16
   648.9 1936.41   699.2 1957.65   739.4 1975.12   779.7    1992   870.2  2028.1
#Mann= 3 , 0 , 0
       0      .1       0   492.8    .045       0   502.8      .1       0
Bank Sta=492.8,502.8
XS Rating Curve= 0 ,0
Exp/Cntr=0.3,0.1

Type RM Length L Ch R = 1 ,1366.8  ,200.9,194.5,188
XS GIS Cut Line= 4
     1835002.179      161241.257     1834713.523      161527.692
     1834720.185      161825.229     1834809.002      162065.035
#Sta/Elev= 30
     9.9 2014.09   158.7 2025.15   178.5 2024.92   198.4 2022.87   218.2  2019.3
     248 2007.27   267.8    2002   287.6 1998.93   347.1 1994.77   376.9 1989.49
   406.7 1981.34   436.4 1962.35   476.1 1934.93   505.9 1917.86   525.7 1909.28
   545.5 1902.52   555.5 1900.46   570.3 1899.44   575.3 1899.41   580.3 1899.71
   605.1 1902.19   624.9 1905.68   674.5 1918.71   773.1 1955.05   812.5 1970.67
   871.5 1991.86   881.3 1994.34     901 1996.88   910.8 1999.88     960 2025.06
#Mann= 3 , 0 , 0
       0      .1       0   570.3    .045       0   580.3      .1       0
Bank Sta=570.3,580.3
XS Rating Curve= 0 ,0
Exp/Cntr=0.3,0.1

Type RM Length L Ch R = 1 ,1172.3  ,96,104.8,113.7
XS GIS Cut Line= 4
     1834504.804      161298.988     1834502.583      161680.902
     1834569.196      161867.417      1834746.83      162100.562
#Sta/Elev= 30
    10.1 2123.93    40.2 2110.48   100.5    2081   170.9 2041.34   251.3 1992.89
   261.3 1988.27   281.4 1982.99   291.5 1979.23   301.5 1973.84   351.8 1943.82
   371.9 1932.86   401.7 1919.42   421.5 1912.11   461.1 1900.69     471 1898.06
   475.9 1897.54   480.9 1897.01   485.9 1897.63   490.8 1898.24   500.8 1901.58
   520.6 1910.15     580 1933.63   741.7 1994.63   761.9  2003.5   782.1 2013.75
   802.3 2025.49   822.5 2038.46   832.6 2044.03   842.8 2048.71   873.1  2058.7
#Mann= 3 , 0 , 0
       0      .1       0   475.9    .045       0   485.9      .1       0
Bank Sta=475.9,485.9
XS Rating Curve= 0 ,0
Exp/Cntr=0.3,0.1

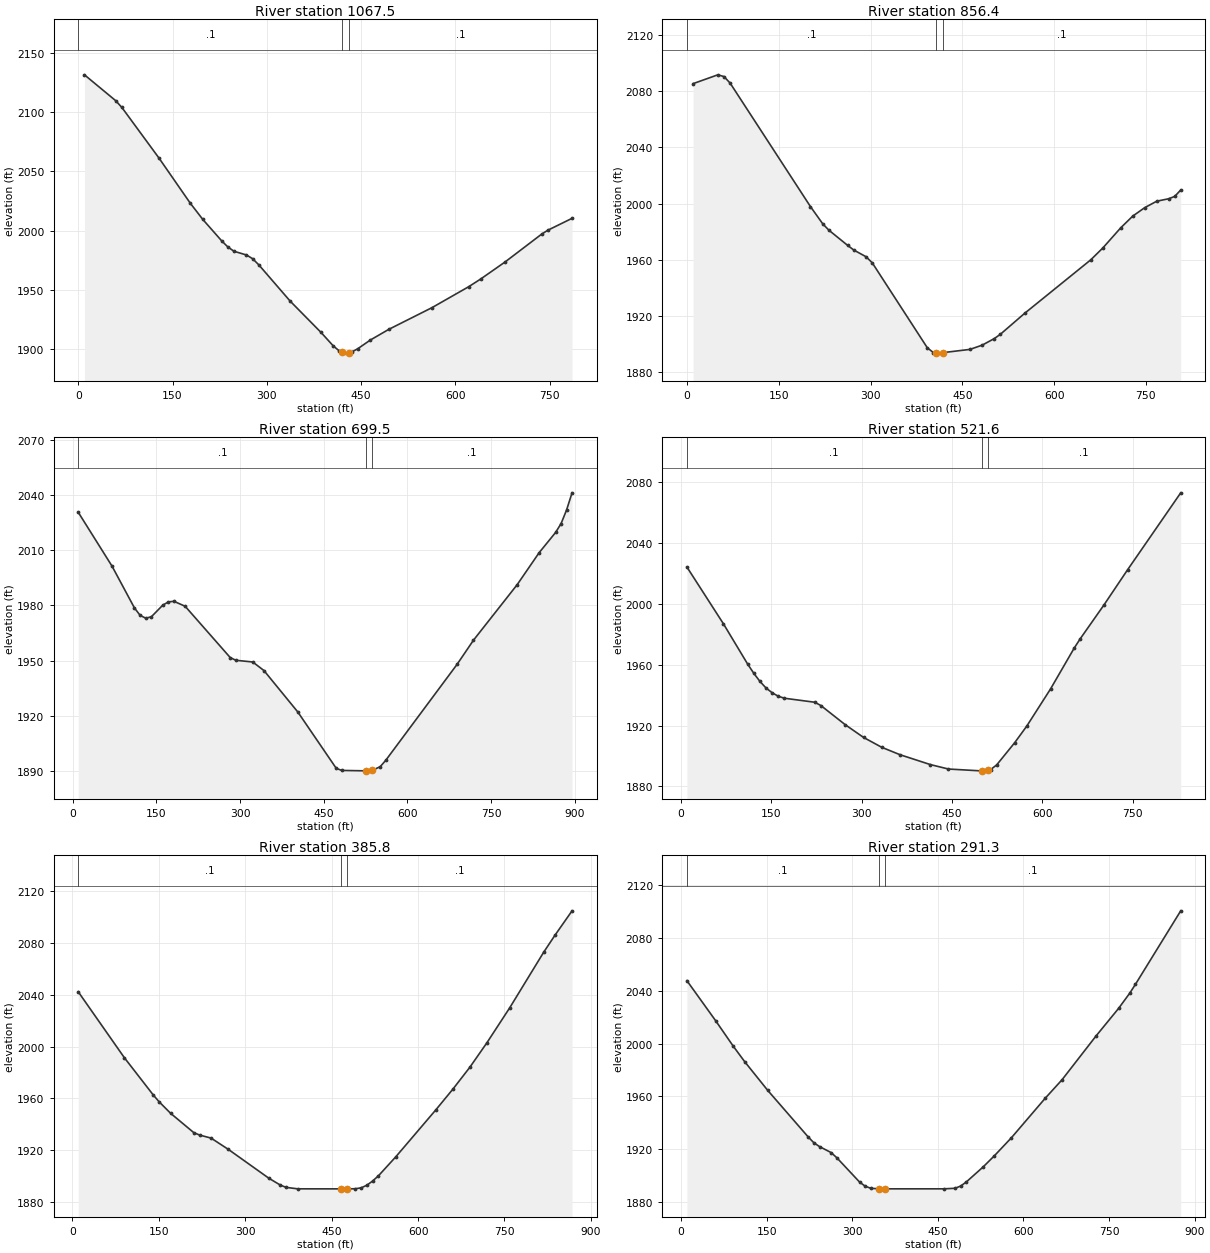
Type RM Length L Ch R = 1 ,1067.5  ,218,211.1,204.2
XS GIS Cut Line= 4
     1834416.819      161333.127     1834444.574      161668.967
      1834422.37      161893.785     1834461.228      162113.052
#Sta/Elev= 30
     9.9 2131.31    59.5 2109.55    69.4 2103.81   128.8 2060.87   178.4 2022.94
   198.2 2009.35     228 1991.42   237.9 1986.22   247.8 1982.51   267.6 1979.39
   277.5 1976.23   287.4 1970.99     337 1940.57   386.1 1914.16   405.7 1902.73
   415.6 1898.33   420.4 1897.49   425.4 1896.62   430.4 1897.09   435.2 1897.55
     445 1900.44   464.7 1907.66   494.1 1916.68   562.9 1935.01     621 1952.58
   640.4 1959.17   679.1 1973.51   737.2 1996.96   746.9 2000.22   785.6  2010.3
#Mann= 3 , 0 , 0
       0      .1       0   420.4    .045       0   430.4      .1       0
Bank Sta=420.4,430.4
XS Rating Curve= 0 ,0
Exp/Cntr=0.3,0.1

Type RM Length L Ch R = 1 ,856.4   ,158.1,156.8,155.5
XS GIS Cut Line= 3
     1834205.879      161369.209     1834261.389      161924.316
     1834394.615      162129.705
#Sta/Elev= 30
    10.1 2085.25    50.5 2091.52    60.6 2090.29    70.6 2085.65   201.9 1997.85
     222 1985.58   232.1 1981.06   262.4 1970.38   272.5 1967.04   292.7 1962.23
   302.8 1957.93   392.8 1897.52   402.7  1894.1   407.7 1893.91   412.7 1893.73
   417.7 1894.05   462.4 1896.38   482.3 1899.38   502.2 1904.06   512.2 1907.15
     552 1922.09   659.9 1960.07   679.5 1968.45   708.8  1982.8   728.4 1991.11
     748 1997.12   767.6  2001.7   787.2 2003.45     797 2005.11   806.8 2009.67
#Mann= 3 , 0 , 0
       0      .1       0   407.7    .045       0   417.7      .1       0
Bank Sta=407.7,417.7
XS Rating Curve= 0 ,0
Exp/Cntr=0.3,0.1

Type RM Length L Ch R = 1 ,699.5   ,172.4,177.9,183.6
XS GIS Cut Line= 4
     1833822.296      161417.811        1834056.      161746.682
     1834122.613      161963.173     1834275.267      162179.665
#Sta/Elev= 30
    10.1 2030.62    70.6 2001.38   110.9 1978.63     121 1974.64   131.1 1973.08
   141.2 1973.89   161.4 1980.12   171.5 1981.93   181.6 1982.27   201.7 1979.56
   282.4 1951.72   292.5 1950.24   322.8 1949.31   342.9 1944.65   403.5 1922.18
   472.4 1891.57   482.2 1890.43   526.5  1890.2  531.32 1890.05   536.5 1890.43
   551.2 1892.47     561 1895.89   688.8 1947.99   718.3 1961.16   796.7 1991.35
     836  2008.7   865.4 2019.65   875.2 2024.44     885 2031.78   894.9 2041.17
#Mann= 3 , 0 , 0
    10.1      .1       0   526.5    .045       0   536.5      .1       0
Bank Sta=526.5,536.5
XS Rating Curve= 0 ,0
Exp/Cntr=0.3,0.1

Type RM Length L Ch R = 1 ,521.6   ,131.7,135.9,139.8
XS GIS Cut Line= 4
     1833778.447      161435.822     1833908.897      161807.743
     1833914.448      162007.582     1834000.489      162226.849
#Sta/Elev= 30
    10.1 2024.28    70.7 1986.94   111.2 1960.25   121.3 1954.27   131.4 1948.99
   141.5 1944.68   151.6 1941.56   161.7  1939.3   171.8 1937.98   222.3 1935.34
   232.4 1933.18   272.9 1920.55   303.2 1912.21   333.5 1905.69   363.8 1900.82
   414.1 1894.34   444.1 1891.41   499.1 1890.17   504.1 1890.03   509.1  1890.6
   514.1 1891.06   524.1 1894.08   554.1 1908.75   574.1 1919.64   613.7 1944.18
   652.9 1971.01   662.8 1977.08     702 1999.21   741.3 2022.41   829.6 2073.08
#Mann= 3 , 0 , 0
    10.1      .1       0   499.1    .045       0   509.1      .1       0
Bank Sta=499.1,509.1
XS Rating Curve= 0 ,0
Exp/Cntr=0.3,0.1

Type RM Length L Ch R = 1 ,385.8   ,96.2,94.5,92.9
XS GIS Cut Line= 4
     1833756.243      161410.842     1833812.598      161726.677
     1833764.569      162013.133     1833806.202      162265.706
#Sta/Elev= 30
      10 2042.39    90.2 1991.41   140.4 1962.62   150.4 1957.46   170.4 1948.54
   210.5 1933.66   220.6 1931.76   240.6 1929.41   270.7 1920.66   340.9 1898.43
   360.9 1893.11   370.9 1891.36   390.9 1890.23   466.1  1890.2  471.42    1890
   476.1  1890.2   491.1 1890.29   501.1 1890.99   511.1 1893.02   521.1 1896.26
   531.2  1900.3   561.2  1914.9     631 1951.31   660.5 1967.25     690 1984.18
   719.6 2003.09     759 2029.95     818 2072.89   837.7 2086.08   867.3 2104.89
#Mann= 3 , 0 , 0
      10      .1       0   466.1    .045       0   476.1      .1       0
Bank Sta=466.1,476.1
XS Rating Curve= 0 ,0
Exp/Cntr=0.3,0.1

Type RM Length L Ch R = 1 ,291.3   ,81.2,82.8,84.3
XS GIS Cut Line= 4
     1833736.814      161408.067     1833708.596      161689.816
     1833678.317      162053.166     1833734.038      162274.033
#Sta/Elev= 30
    10.1  2047.5    60.7 2017.11      91  1998.2   111.2 1986.39   151.7 1964.64
   222.5  1929.5   232.6 1925.02   242.7 1922.08   262.9  1917.6     273 1913.63
   312.7 1895.34   322.6 1892.18   332.4 1890.62   347.1 1890.21  352.39 1889.98
   357.1  1890.2   460.5  1890.2   480.2 1890.62   490.1 1892.36     500 1895.47
   529.5 1906.83   549.2 1915.27   578.8 1928.78   637.9 1958.56   667.6 1972.64
     727 2005.62   766.6  2026.5   786.4 2038.14   796.3 2044.79   875.6 2100.28
#Mann= 3 , 0 , 0
    10.1      .1       0   347.1    .045       0   357.1      .1       0
Bank Sta=347.1,357.1
XS Rating Curve= 0 ,0
Exp/Cntr=0.3,0.1

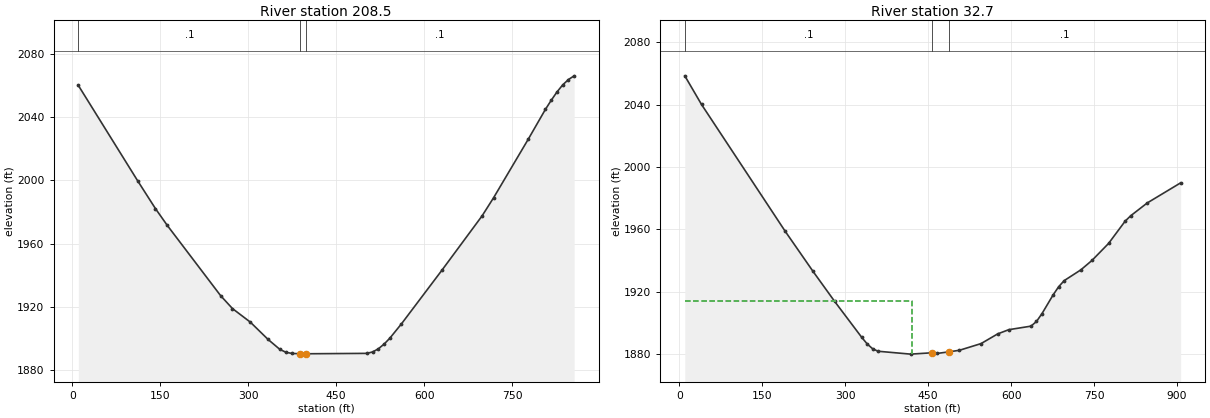
Type RM Length L Ch R = 1 ,208.5   ,174.8,175.8,176.8
XS GIS Cut Line= 4
      1833689.63       161399.74     1833628.568      161768.886
     1833586.935      162021.459     1833606.364      162246.277
#Sta/Elev= 30
    10.1 2060.17   111.2  1999.8   141.6 1982.16   161.8 1971.51   252.8    1927
     273 1918.82   303.4 1910.26   333.7 1899.29   353.9 1892.95     364 1891.18
   374.2 1890.41   388.9 1890.21  394.17 1889.97   398.9  1890.2   502.2 1890.45
     512 1891.35   521.8 1893.32   531.7 1896.35   541.5 1900.11   561.2 1909.13
   630.1 1943.04   698.8 1977.56   718.4 1989.03   777.3 2025.97   806.7 2044.94
   816.6 2050.69   826.4 2055.97   836.2 2060.47     846 2063.87   855.8 2066.24
#Mann= 3 , 0 , 0
    10.1      .1       0   388.9    .045       0   398.9      .1       0
Bank Sta=388.9,398.9
XS Rating Curve= 0 ,0
Exp/Cntr=0.3,0.1

Type RM Length L Ch R = 1 ,32.7    ,28.3,32.7,37.1
XS GIS Cut Line= 4
     1833631.419      161396.808     1833495.342      161596.803
     1833431.505      161893.785     1833475.914      162251.829
#Sta/Elev= 30
    10.1 2058.55    40.3 2040.19   191.5 1958.87   241.9  1933.1   281.1 1913.78
   330.1  1890.7   339.9 1886.51   349.7 1883.44   359.5 1881.85   418.3    1880
   457.5 1880.87  466.84 1880.47   486.9 1881.43   506.5 1882.46   545.7 1886.76
   575.7 1892.97   595.8 1895.68   635.9 1897.95   645.9 1900.94   655.9 1906.01
   675.9 1917.95     686 1923.23     696 1927.16   726.1 1934.06   746.1 1940.07
   776.2 1950.99   806.2 1965.31   816.3 1968.79   846.3 1977.03   906.5 1989.88
#Mann= 3 , 0 , 0
    10.1      .1       0   457.5    .045       0   486.9      .1       0
#XS Ineff= 2 , 0
          421.23 1914.24
Permanent Ineff=
       F       F
Bank Sta=457.5,486.9
XS Rating Curve= 0 ,0
Exp/Cntr=0.3,0.1

Chan Stop Cuts=-1
Use User Specified Reach Order=0